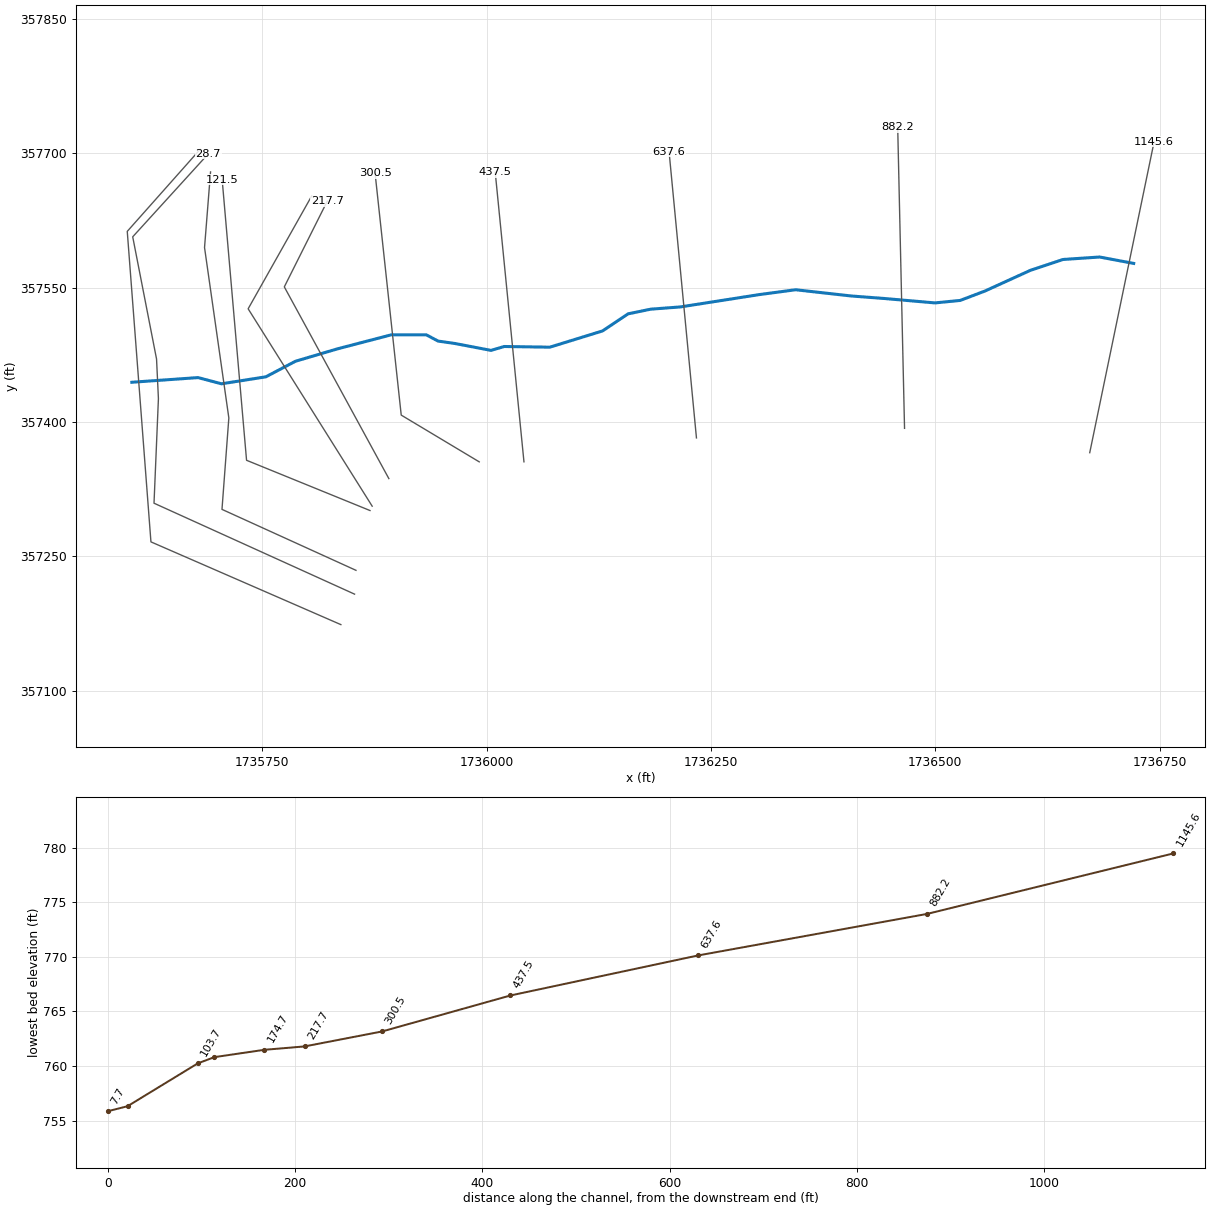
--- BIASBR.prj (project) ---

Proj Title=BIASBR
Current Plan=p01
Default Exp/Contr=0,0
English Units
Geom File=g01
Flow File=f01
Plan File=p01
BEGIN DESCRIPTION:
END DESCRIPTION:
DSS Export Rating Curves= 0
DSS Export Rating Curve Sorted= 0
DSS Export Volume Flow Curves= 0
DXF OffsetX= 0
DXF OffsetY= 0
DXF ScaleX= 0
DXF ScaleY= 0

--- BIASBR.p01 (plan) ---

Plan Title=Floodplain
Program Version=4.00
Geom File=g01
Flow File=f01
K Sum by GR=0
Std Step Tol=0.01
Critical Tol=0.01
Num of Std Step Trials=20
Max Error Tol=0.3
Flow Tol Ratio=0.001
Split Flow NTrial=30
Split Flow Tol=0.02
Split Flow Ratio=0.02
Log Output Level=0
Friction Slope Method=1
Unsteady Friction Slope Method=2
Unsteady Bridges Friction Slope Method=1
Global Log Level=0
CheckData=False
Run HTab=0
Run UNet=0
Run PostProcess=0
UNET Theta=0
UNET Theta Warmup=0
UNET ZTol=0
UNET ZSATol=0
UNET MxIter=0
UNET MaxInSteps=0
UNET DtIC=0
UNET DtMin=0
UNET MaxCRTS=0
UNET WFStab=0
UNET SFStab=0
UNET WFX=0
UNET SFX=0
UNET DSS MLevel=0
UNET DZMax Abort=0
UNET Convert EG Bridges=0
UNET Use Existing IB Tables=0
UNET Froude Limit=0
UNET Froude Power=0
Write IC File=0
Echo Input=False
Echo Output=False
Write Detailed=0

--- BIASBR.f01 (steady flow) ---

Flow Title=NFF Regression Equation
Program Version=4.00
Number of Profiles=1
Profile Names=P100yr
River Rch & RM=BIASBR,Main      ,1145.6
1000.448
River Rch & RM=BIASBR,Main      ,437.5
1005.514
River Rch & RM=BIASBR,Main      ,217.7
1101.978
Boundary for River Rch & Prof#=BIASBR,Main      ,1
Up Type=0
Dn Type=3
Dn Slope=0.027115

--- BIASBR.g01 (geometry) ---

Geom Title=USGS 10m DEM
Program Version=4.10

River Reach=BIASBR          ,Main
Reach XY= 28
     1736721.096      357576.988     1736683.078      357584.151
     1736642.306      357581.396     1736605.941      357569.274
     1736555.251      357546.133     1736527.702      357535.665
     1736499.602       357532.91     1736442.852      357537.868
     1736406.487      357540.623     1736344.303      357547.607
     1736305.241      357542.398       1736215.8      357528.406
     1736182.845      357525.906     1736157.671      357520.697
     1736129.221      357501.633     1736070.502      357483.475
      1736019.65      357484.239     1736004.893      357479.899
     1735964.095      357487.711     1735945.866      357490.315
     1735932.845       357497.26     1735893.782       357497.26
     1735833.887      357481.635     1735787.011      357467.746
     1735754.025      357450.385     1735704.546      357442.572
     1735678.505      357449.516      1735604.72      357444.308

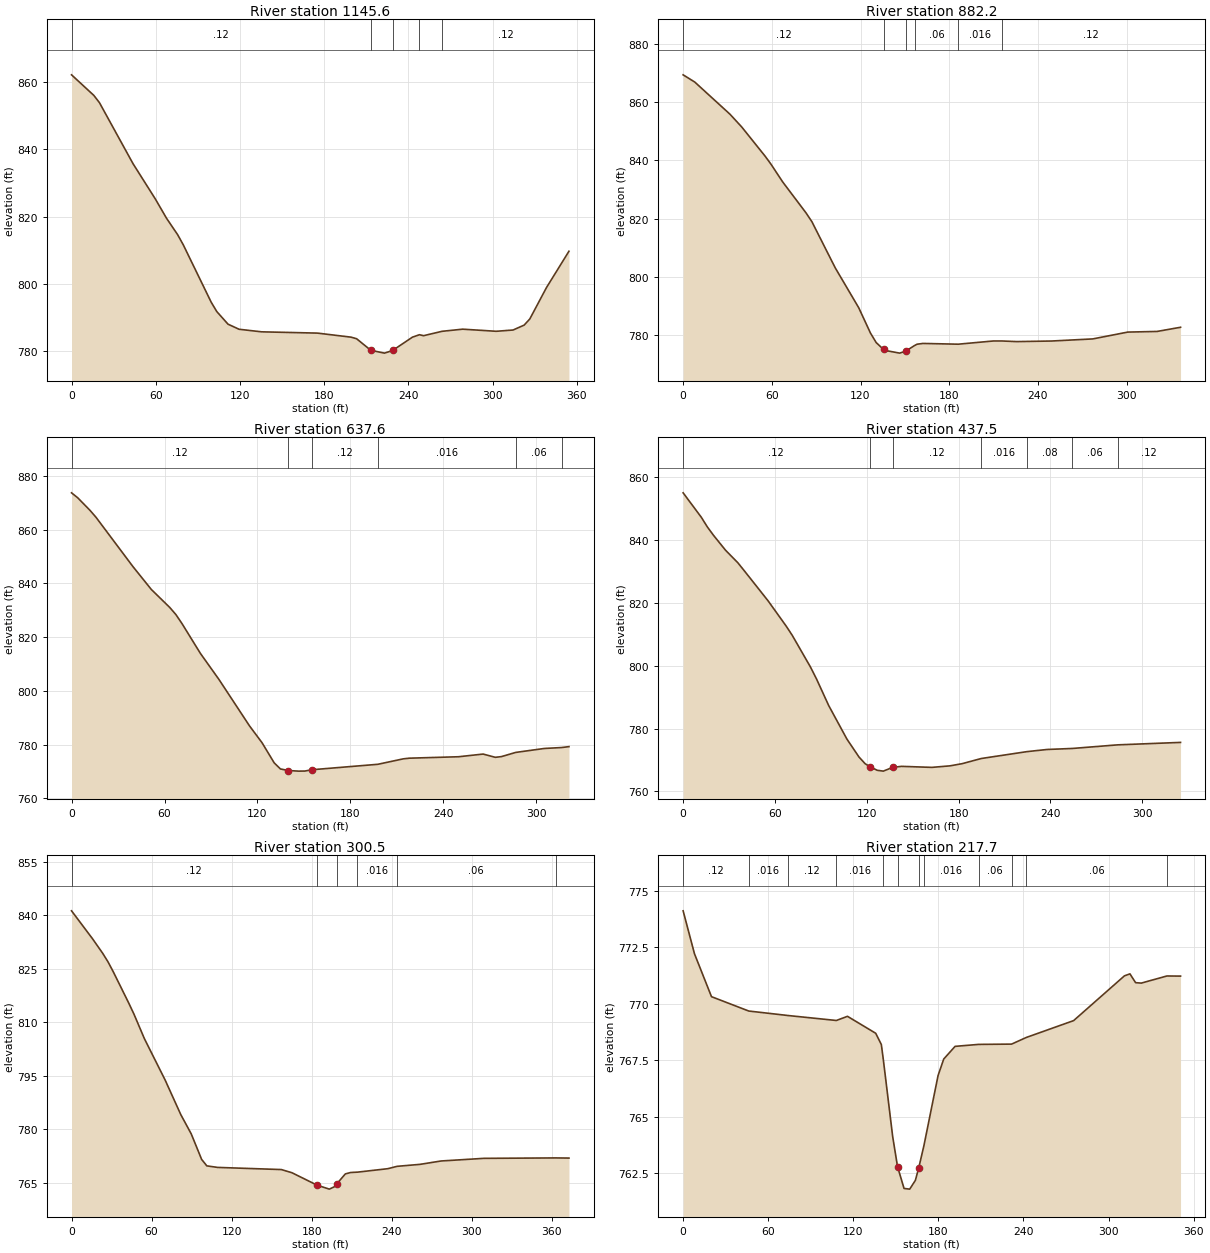
Type RM Length L Ch R = 1 ,1145.6  ,254.8,263.3,271.8
XS GIS Cut Line= 2
     1736672.079      357365.651     1736743.776      357712.698
#Sta/Elev= 30
       0  862.17    15.9  856.05    19.9  853.89    43.8  835.77    59.7  825.28
    67.7  819.53    75.6  814.66    79.6  811.66    99.5   794.6   103.5  791.81
   111.5  788.06   119.4  786.55   135.4  785.79   175.2  785.41   199.1  784.21
   203.1  783.74  213.27780.2892     223  779.46  228.75780.2418   242.9  784.21
   247.9784.9301   250.8  784.64  263.98785.9437   278.7  786.58   302.6  785.95
   314.6  786.33   322.5  787.79   326.5  789.61   338.4  798.95   354.4  809.74
#Mann= 5 ,-1 , 0
       0     .12       0  213.27    .045       0  228.75    .016       0
   247.9     .08       0  263.98     .12       0
Bank Sta=213.27,228.75
XS Rating Curve= 0 ,0
Exp/Cntr=0.3,0.1

Type RM Length L Ch R = 1 ,882.2   ,241.8,244.6,247.3
XS GIS Cut Line= 2
     1736465.716      357392.848     1736458.089      357729.217
#Sta/Elev= 30
       0   869.3     7.9  866.81    31.7   855.8    39.6  851.45    55.4  841.47
    59.4   838.7    67.3  832.63    83.1  822.01    87.1  818.98   102.9  803.15
   118.8  789.47   126.7  780.83   130.6  777.54   134.6  775.64   135.8  775.34
   138.5  774.67   146.5  773.92   150.8  774.66  156.55776.5223   158.3  776.98
   162.3  777.24   186.1776.9822   209.8  778.08  215.64778.0828   225.6  777.87
   249.4  778.07   277.1  778.79   300.8  781.13   320.6  781.35   336.5  782.78
#Mann= 6 ,-1 , 0
       0     .12       0   135.8    .045       0   150.8     .12       0
  156.55     .06       0   186.1    .016       0  215.64     .12       0
Bank Sta=135.8,150.8
XS Rating Curve= 0 ,0
Exp/Cntr=0.3,0.1

Type RM Length L Ch R = 1 ,637.6   ,199.8,200.2,200.3
XS GIS Cut Line= 2
     1736233.843       357382.17     1736203.333      357701.758
#Sta/Elev= 30
       0  873.72       4  871.87    11.9  867.21    15.8  864.61    39.6  846.28
    51.5  837.74    63.4  831.04    67.4  828.36    71.3  825.03    83.2  813.91
    95.1  804.28   114.9  786.92   122.9  780.73   130.8  773.19   134.8  770.93
     140  770.34   146.6  770.12   150.6  770.15     155  770.63  197.63772.6586
     214  774.68     218  774.94   249.7  775.47   265.6  776.47   273.5  775.26
   277.4  775.52  286.64777.0831   305.2  778.56  316.31778.9023     321  779.24
#Mann= 6 ,-1 , 0
       0     .12       0     140    .045       0     155     .12       0
  197.63    .016       0  286.64     .06       0  316.31     .12       0
Bank Sta=140,155
XS Rating Curve= 0 ,0
Exp/Cntr=0.3,0.1

Type RM Length L Ch R = 1 ,437.5   ,136.6,137,137.3
XS GIS Cut Line= 2
     1736041.632      357355.474     1736009.597      357678.876
#Sta/Elev= 30
       0  854.92    11.9  847.14    15.8   844.1    19.8  841.45    27.7  836.68
    35.7  832.72    39.6  830.37    55.5   820.6    67.4  812.51    71.3  809.62
    83.2  799.56    87.2  795.71    95.1  787.32     107  776.66   114.9  770.95
   118.9  768.83   121.8  767.93   126.8  766.73   130.8  766.46   136.8  767.64
   142.7  767.98   162.5  767.65   174.4  768.14   182.3  768.83  194.85770.4752
  224.53772.6475   237.8  773.34  254.21773.6615  283.89774.8085     325  775.59
#Mann= 7 ,-1 , 0
       0     .12       0   121.8    .045       0   136.8     .12       0
  194.85    .016       0  224.53     .08       0  254.21     .06       0
  283.89     .12       0
Bank Sta=121.8,136.8
XS Rating Curve= 0 ,0
Exp/Cntr=0.3,0.1

Type RM Length L Ch R = 1 ,300.5   ,67.8,82.8,97.5
XS GIS Cut Line= 3
     1735991.775      357355.437     1735904.873      357407.638
      1735875.75      357677.547
#Sta/Elev= 30
       0   841.3    15.6  833.53    23.4  829.35    27.3     827    31.2  824.25
    42.9  815.39    46.8  812.29    54.6  805.42    70.2  793.76    81.9  784.08
    89.7  778.69    97.5  771.52   101.4   769.7   109.4  769.27   157.3  768.66
   165.2  767.77     184  764.29   193.2  763.17   197.2  763.87     199  764.73
   205.2  767.44   209.2  767.84  214.24767.9352   237.1  768.91  243.94769.5672
   261.1  770.12     277  771.07     309  771.81  362.77  771.93   372.8  771.89
#Mann= 6 ,-1 , 0
       0     .12       0     184    .045       0     199     .12       0
  214.24    .016       0  243.94     .06       0  362.77     .12       0
Bank Sta=184,199
XS Rating Curve= 0 ,0
Exp/Cntr=0.3,0.1

Type RM Length L Ch R = 1 ,217.7   ,40.9,43,45.3
XS GIS Cut Line= 3
     1735891.068      357336.747     1735774.589      357550.806
     1735822.506      357646.639
#Sta/Elev= 30
       0  774.12       8  772.22      20  770.32   46.28 769.684   73.95769.4857
  108.07769.2656   115.9  769.45   135.8   768.7   139.8   768.2  141.21767.5232
   147.8  764.12   151.2   762.8   155.8  761.83   159.8   761.8   163.8  762.19
   166.2  762.75  169.86763.7377   179.8  766.83   183.8  767.56   191.8  768.12
  208.46768.2071  231.65768.2197  242.08768.5152   275.4  769.26   311.2  771.24
   315.1  771.33   319.1  770.94   323.1  770.92  341.18771.2357   350.8  771.23
#Mann= 12 ,-1 , 0
       0     .12       0   46.28    .016       0   73.95     .12       0
  108.07    .016       0  141.21     .12       0   151.2    .045       0
   166.2     .12       0  169.86    .016       0  208.46     .06       0
  231.65    .016       0  242.08     .06       0  341.18     .12       0
Bank Sta=151.2,166.2
XS Rating Curve= 0 ,0
Exp/Cntr=0.3,0.1

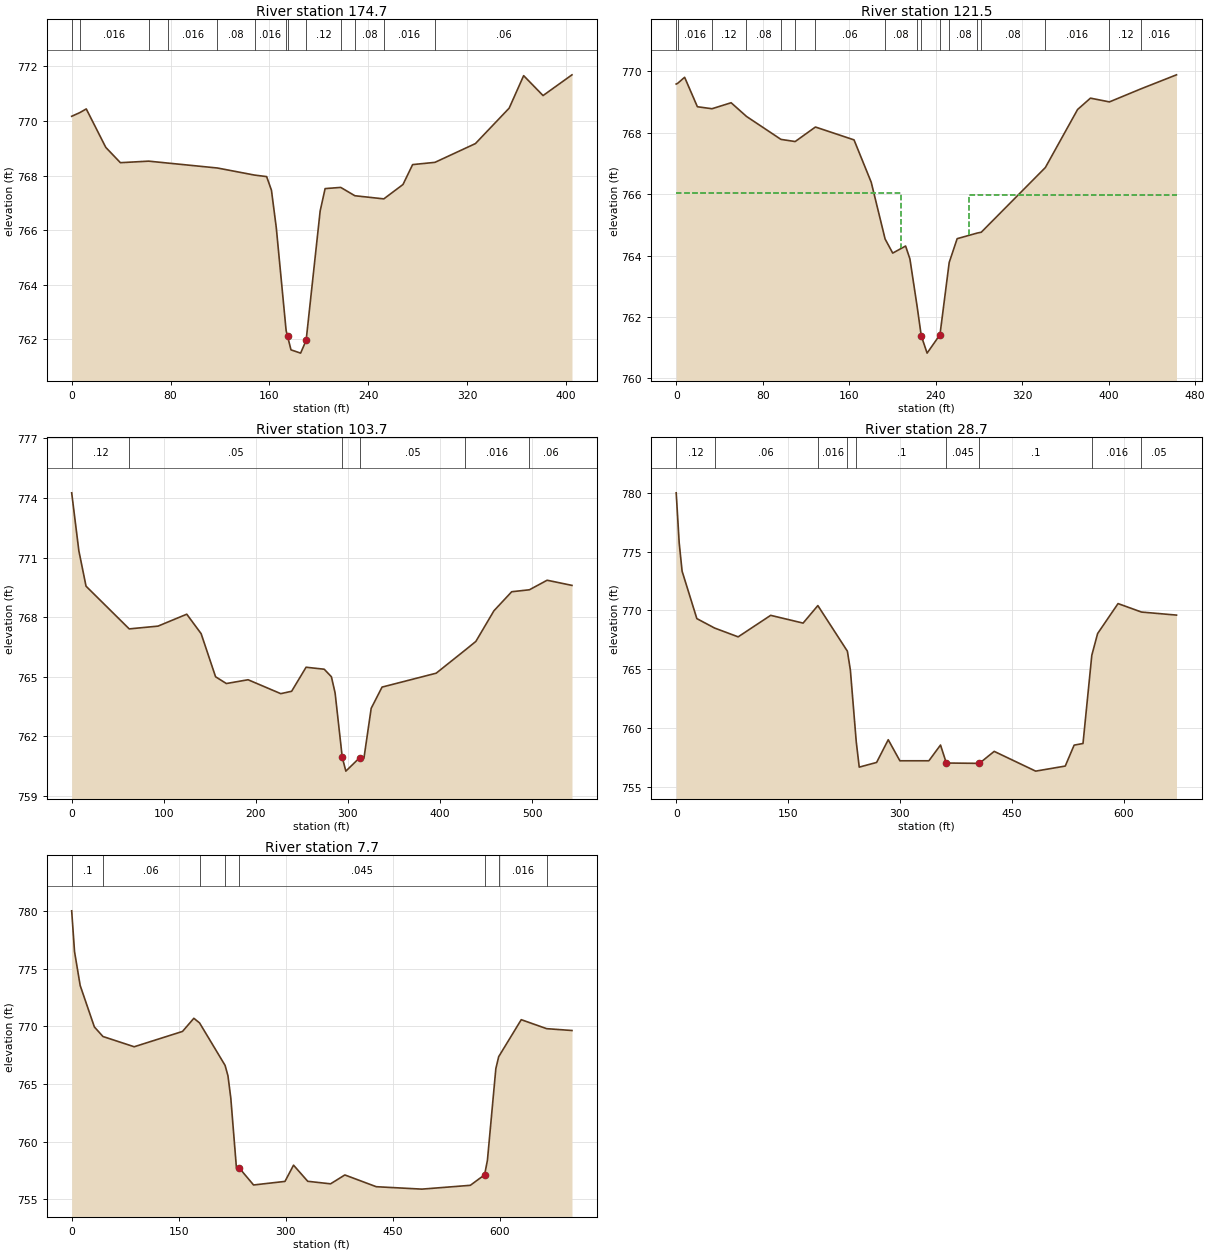
Type RM Length L Ch R = 1 ,174.7   ,71.1,53.3,35.4
XS GIS Cut Line= 3
     1735872.505      357305.944     1735734.297       357526.33
      1735805.13      357652.372
#Sta/Elev= 30
       0  770.17     6.7 770.308    11.8  770.44    27.6  769.03    39.4  768.47
   62.29768.5261   78.17768.4538  117.88 768.275   147.9768.0157   157.7  767.96
   161.6  767.46   165.5  766.09  173.46762.3192  174.67762.1005   177.4  761.61
   185.2  761.49  189.66761.9584     201   766.7     205  767.52  217.63767.5636
  229.05767.2588  252.49767.1435     268  767.67   275.8   768.4  293.85768.4819
   326.6  769.17   353.9  770.47   365.6  771.66   381.3  770.93   404.7  771.69
#Mann= 13 ,-1 , 0
       0     .12       0     6.7    .016       0   62.29     .08       0
   78.17    .016       0  117.88     .08       0   147.9    .016       0
  173.46     .12       0  174.67    .045       0  189.66     .12       0
  217.63    .016       0  229.05     .08       0  252.49    .016       0
  293.85     .06       0
Bank Sta=174.67,189.66
XS Rating Curve= 0 ,0
Exp/Cntr=0.3,0.1

Type RM Length L Ch R = 1 ,121.5   ,15.7,17.8,20.2
XS GIS Cut Line= 3
     1735870.071      357301.075     1735732.525      357357.179
     1735705.365      357670.245
#Sta/Elev= 30
       0  769.59    1.22769.6088     7.8  769.81    19.6  768.85   33.11 768.785
    50.8  768.98   65.01768.5349   96.91767.7859  110.05767.7155   128.8 768.189
   164.5  767.77   180.4  766.39  193.25764.5392   200.3  764.08   212.2  764.31
   216.2  763.89   222.9762.3354  226.68761.3873   232.1  760.82     244  761.42
  252.54 763.775   259.9  764.55   278.7764.7355  282.19764.7599  341.48766.8683
   371.3  768.76   383.2  769.13  400.77769.0079  430.42  769.44   462.8  769.89
#Mann= 17 ,-1 , 0
       0     .12       0    1.22    .016       0   33.11     .12       0
   65.01     .08       0   96.91     .06       0  110.05     .08       0
   128.8     .06       0  193.25     .08       0   222.9     .06       0
  226.68    .045       0     244     .06       0  252.54     .08       0
   278.7     .06       0  282.19     .08       0  341.48    .016       0
  400.77     .12       0  430.42    .016       0
#XS Ineff= 2 , 0
          208.13  766.05  270.81          765.98
Permanent Ineff=
       F       F
Bank Sta=226.68,244
XS Rating Curve= 0 ,0
Exp/Cntr=0.3,0.1

Type RM Length L Ch R = 1 ,103.7   ,80.2,75,72.9
XS GIS Cut Line= 5
     1735854.447      357234.307     1735705.142      357302.363
     1735712.781      357404.446     1735685.697      357594.724
     1735692.383       357679.17
#Sta/Elev= 30
       0  774.26     7.8  771.34    15.6  769.56    62.5  767.41    93.8  767.55
     125  768.15   140.6  767.17   156.3     765     168  764.66   191.6  764.85
   227.1  764.15   238.9  764.27   254.6  765.48   274.3  765.38   282.1     765
   286.1  764.19   293.9  760.94   297.8  760.25   312.9  760.93   317.4  760.89
   325.3  763.41   337.1  764.48   395.9  765.18   427.3  766.34     439  766.78
   458.6  768.32   477.9  769.28   497.2  769.38   516.4  769.86   543.4   769.6
#Mann= 6 ,-1 , 0
       0     .12       0    62.5     .05       0   293.9    .045       0
   312.9     .05       0   427.3    .016       0   497.2     .06       0
Bank Sta=293.9,312.9
XS Rating Curve= 0 ,0
Exp/Cntr=0.3,0.1

Type RM Length L Ch R = 1 ,28.7    ,18.4,21,20.1
XS GIS Cut Line= 6
     1735852.875      357207.717       1735629.4      357309.262
     1735634.308      357425.974     1735632.225      357470.245
     1735605.662      357606.703     1735689.949      357699.454
#Sta/Elev= 30
       0     780       4  775.76     7.9  773.34    27.7   769.3    51.5   768.5
    83.1  767.75   126.7  769.58   170.2  768.92     190  770.41   229.6  766.53
   233.6  764.93   241.5  758.82   245.5  756.67   268.8  757.07   284.4     759
     300  757.21   338.9  757.21   354.5  758.55   362.3  757.02   406.6  756.99
   426.5  758.01   482.1  756.33   521.8  756.76   533.7  758.54   545.6  758.68
   557.4  766.18   565.2  768.03   592.6  770.58     624  769.86     671   769.6
#Mann= 9 ,-1 , 0
       0     .12       0    51.5     .06       0     190    .016       0
   229.6     .05       0   241.5      .1       0   362.3    .045       0
   406.6      .1       0   557.4    .016       0     624     .05       0
Bank Sta=362.3,406.6
XS Rating Curve= 0 ,0
Exp/Cntr=0.3,0.1

Type RM Length L Ch R = 1 ,7.7     ,7.9,7.7,7.5
XS GIS Cut Line= 4
     1735837.616      357173.692     1735625.975      357266.078
     1735599.586      357612.779     1735680.836      357704.446
#Sta/Elev= 30
       0  780.03       4  776.49    11.9  773.55    31.8  769.95    43.8  769.12
    87.6  768.23   155.3  769.56   171.2   770.7   179.2   770.3     215  766.61
     219  765.71     223  763.77   230.9   757.7   234.9   757.7   254.9  756.23
   298.9  756.54   310.9  757.95   330.8  756.55   362.8  756.33   382.8   757.1
   426.8  756.08   490.7  755.87   558.6   756.2   578.6  757.11   582.6  758.37
   594.4  766.33   598.4  767.37     630  770.58   665.6   769.8   701.1  769.64
#Mann= 8 ,-1 , 0
       0      .1       0    43.8     .06       0   179.2    .016       0
     215     .05       0   234.9    .045       0   578.6      .1       0
   598.4    .016       0   665.6     .05       0
Bank Sta=234.9,578.6
XS Rating Curve= 0 ,0
Exp/Cntr=0.3,0.1

Chan Stop Cuts=-1
Use User Specified Reach Order=0
Composite Channel Slope=5